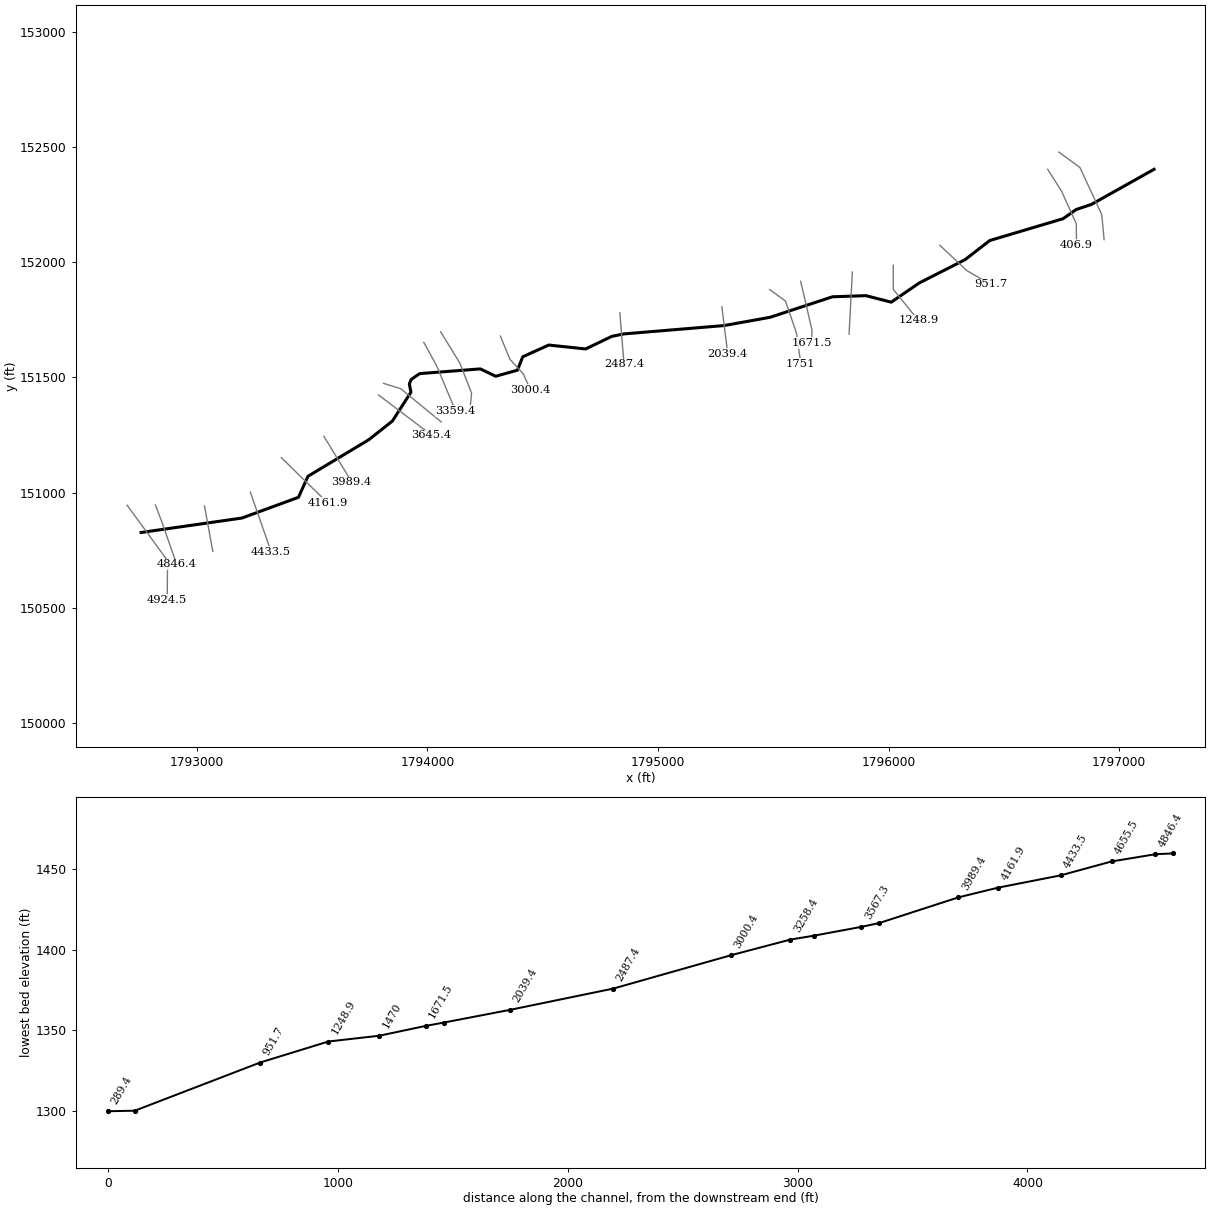
--- Little Indian Creek.prj (project) ---

Proj Title=Little Indian Creek
Current Plan=p01
Default Exp/Contr=0,0
English Units
Geom File=g01
Flow File=f01
Plan File=p01
BEGIN DESCRIPTION:
END DESCRIPTION:
DSS Export Rating Curves= 0
DSS Export Rating Curve Sorted= 0
DSS Export Volume Flow Curves= 0
DXF OffsetX= 0
DXF OffsetY= 0
DXF ScaleX= 0
DXF ScaleY= 0

--- Little Indian Creek.p01 (plan) ---

Plan Title=Floodplain
Program Version=4.00
Geom File=g01
Flow File=f01
K Sum by GR=0
Std Step Tol=0.01
Critical Tol=0.01
Num of Std Step Trials=20
Max Error Tol=0.3
Flow Tol Ratio=0.001
Split Flow NTrial=30
Split Flow Tol=0.02
Split Flow Ratio=0.02
Log Output Level=0
Friction Slope Method=1
Unsteady Friction Slope Method=2
Unsteady Bridges Friction Slope Method=1
Global Log Level=0
CheckData=False
Run HTab=0
Run UNet=0
Run PostProcess=0
UNET Theta=0
UNET Theta Warmup=0
UNET ZTol=0
UNET ZSATol=0
UNET MxIter=0
UNET MaxInSteps=0
UNET DtIC=0
UNET DtMin=0
UNET MaxCRTS=0
UNET WFStab=0
UNET SFStab=0
UNET WFX=0
UNET SFX=0
UNET DSS MLevel=0
UNET DZMax Abort=0
UNET Convert EG Bridges=0
UNET Use Existing IB Tables=0
UNET Froude Limit=0
UNET Froude Power=0
Write IC File=0
Echo Input=False
Echo Output=False
Write Detailed=0

--- Little Indian Creek.f01 (steady flow) ---

Flow Title=NFF Regression Equation
Program Version=4.00
Number of Profiles=1
Profile Names=P100yr
River Rch & RM=Little Indian...,Main      ,4924.5
536.8886
River Rch & RM=Little Indian...,Main      ,4433.5
540.0941
River Rch & RM=Little Indian...,Main      ,4161.9
683.3648
River Rch & RM=Little Indian...,Main      ,3645.4
705.5343
River Rch & RM=Little Indian...,Main      ,3258.4
777.6193
River Rch & RM=Little Indian...,Main      ,1470
845.8980
River Rch & RM=Little Indian...,Main      ,289.4
912.5824
Boundary for River Rch & Prof#=Little Indian...,Main      ,1
Up Type=0
Dn Type=3
Dn Slope=0.033425

--- Little Indian Creek.g01 (geometry) ---

Geom Title=Geometry
Program Version=4.00

River Reach=Little Indian...,Main
Reach XY= 30
     1792758.349      150827.662     1793195.957      150890.455
     1793440.788      150980.211     1793481.954       151071.43
     1793745.468      151229.752     1793848.403      151311.216
     1793928.604      151436.254     1793921.658       151472.25
     1793929.844       151491.35     1793966.473       151516.69
     1794229.317      151537.127     1794296.203      151505.205
     1794390.235      151531.611       1794413.6       151589.71
     1794526.062      151640.559     1794686.121      151623.666
     1794799.527      151678.127     1794851.866      151688.856
      1795286.31      151725.061     1795485.897      151760.848
     1795756.813       151849.89     1795902.018       151854.72
     1796011.484      151826.483     1796132.163      151909.348
     1796331.542      152010.757      1796438.68      152093.832
     1796756.407      152188.368      1796813.95      152228.471
     1796879.858      152250.573     1797151.258      152402.722

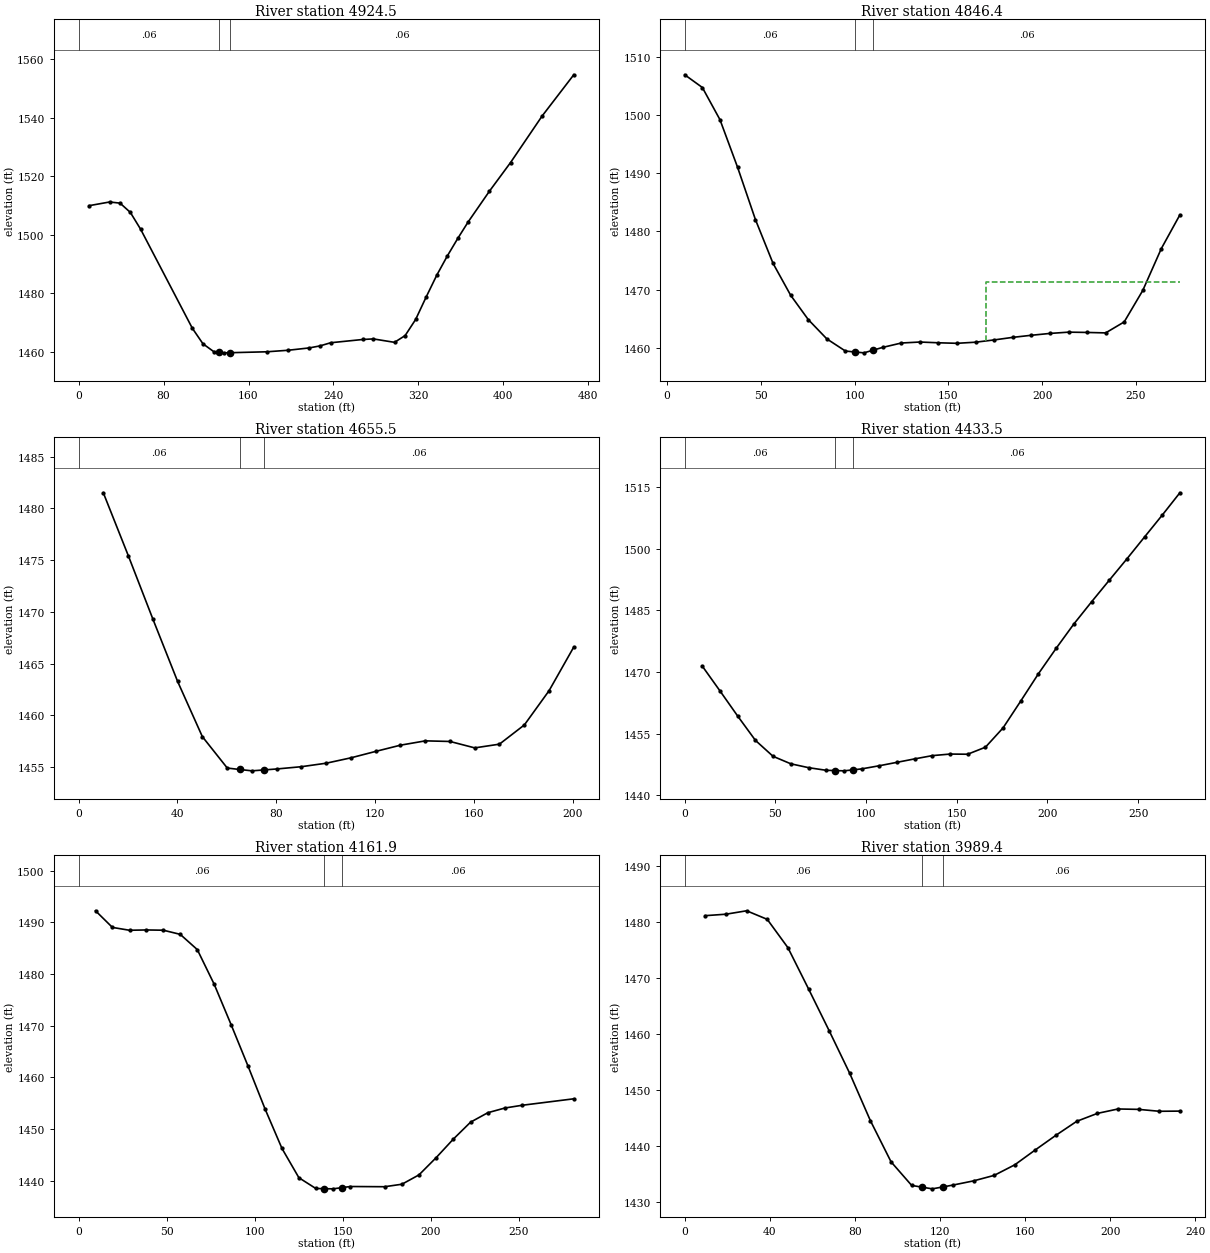
Type RM Length L Ch R = 1 ,4924.5  ,84.7,78.1,71.6
XS GIS Cut Line= 4
     1792697.879      150945.723     1792761.228      150859.337
     1792873.228      150705.349     1792871.538      150536.562
#Sta/Elev= 30
     9.7 1509.89    29.2 1511.16      39 1510.77    48.7 1507.61    58.4 1501.85
   107.1 1468.01   117.1  1462.7   127.2 1460.04   132.2 1459.83   137.2 1459.61
   142.2 1459.65   177.3 1459.97   197.3 1460.49   217.4  1461.3   227.4 1461.99
   237.4 1463.06   267.5 1464.17   277.5 1464.37   297.5  1463.2   307.5 1465.51
   317.4 1471.02   327.3 1478.69   337.3 1486.15   347.2  1492.7   357.1 1498.73
     367 1504.43   386.9 1514.86   406.8 1524.65   436.5 1540.54   466.3 1554.63
#Mann= 3 , 0 , 0
       0     .06       0   132.2    .045       0   142.2     .06       0
Bank Sta=132.2,142.2
XS Rating Curve= 0 ,0
Exp/Cntr=0.3,0.1

Type RM Length L Ch R = 1 ,4846.4  ,194.1,190.9,187.7
XS GIS Cut Line= 3
     1792820.259      150947.163      1792847.24      150876.864
     1792912.728      150689.756
#Sta/Elev= 30
     9.4 1506.96    18.8 1504.77    28.2 1499.23    37.6 1491.03    47.1 1482.05
    56.5 1474.51    65.9 1469.02    75.3 1464.83    85.2 1461.51    95.1 1459.42
     100 1459.26     105 1459.11     110 1459.58   114.9 1460.04   124.9  1460.8
   134.8 1460.97   144.7 1460.84   154.6 1460.75   164.5 1460.94   174.4 1461.33
   184.3 1461.77   194.2 1462.13   204.2 1462.45   214.1 1462.67     224 1462.62
   233.9 1462.54   243.8 1464.43   253.7 1469.84   263.6 1477.05   273.5 1482.85
#Mann= 3 , 0 , 0
     9.4     .06       0     100    .045       0     110     .06       0
#XS Ineff= 2 , 0
                          170.23         1471.31
Permanent Ineff=
       F       F
Bank Sta=100,110
XS Rating Curve= 0 ,0
Exp/Cntr=0.3,0.1

Type RM Length L Ch R = 1 ,4655.5  ,218.8,222,225.1
XS GIS Cut Line= 2
     1793033.345      150942.844      1793069.34      150745.595
#Sta/Elev= 22
      10 1481.52    20.1 1475.45    30.1 1469.29    40.1 1463.27    50.1 1457.94
    60.2  1454.9    65.2 1454.76    70.2 1454.63    75.2 1454.72    80.2 1454.81
    90.2 1455.03   100.3 1455.37   110.3 1455.89   120.3 1456.51   130.3 1457.11
   140.4 1457.53   150.4 1457.47   160.4 1456.85   170.4 1457.21   180.5 1459.07
   190.5 1462.38   200.5  1466.6
#Mann= 3 , 0 , 0
       0     .06       0    65.2    .045       0    75.2     .06       0
Bank Sta=65.2,75.2
XS Rating Curve= 0 ,0
Exp/Cntr=0.3,0.1

Type RM Length L Ch R = 1 ,4433.5  ,261.6,271.6,281.6
XS GIS Cut Line= 3
     1793232.228       151002.65     1793277.199      150873.771
     1793322.169      150744.891
#Sta/Elev= 30
     9.7 1471.45    19.5 1465.39    29.2 1459.31      39 1453.39    48.7 1449.52
    58.5  1447.7    68.3 1446.76      78 1446.12    82.8 1446.06    87.8 1445.99
    92.8 1446.23    97.5 1446.46   107.3 1447.23     117 1448.06   126.8  1448.9
   136.5 1449.69   146.3 1450.07     156 1450.03   165.8 1451.74   175.5 1456.43
   185.3 1462.99     195  1469.6   204.8  1475.8   214.5 1481.68   224.3 1487.09
     234 1492.31   243.8 1497.55   253.5 1502.86   263.3  1508.2     273 1513.62
#Mann= 3 , 0 , 0
       0     .06       0    82.8    .045       0    92.8     .06       0
Bank Sta=82.8,92.8
XS Rating Curve= 0 ,0
Exp/Cntr=0.3,0.1

Type RM Length L Ch R = 1 ,4161.9  ,177.5,172.5,167.6
XS GIS Cut Line= 3
     1793366.367      151152.617       1793462.5        151058.2
     1793567.796      150956.419
#Sta/Elev= 28
     9.6 1492.21    19.2 1488.99    28.9 1488.44    38.5  1488.5    48.1 1488.45
    57.7 1487.65    67.4  1484.7      77 1477.99    86.6 1470.18    96.2 1462.17
   105.9 1453.85   115.5 1446.22   125.1 1440.56   134.7 1438.48   139.5 1438.44
   144.5 1438.41   149.5 1438.64   154.3 1438.86   173.8 1438.82   183.6  1439.3
   193.3 1441.11   203.1 1444.46   212.8 1448.03   222.6 1451.31   232.4 1453.14
   242.1 1454.05   251.9 1454.58   281.2 1455.83
#Mann= 3 , 0 , 0
       0     .06       0   139.5    .045       0   149.5     .06       0
Bank Sta=139.5,149.5
XS Rating Curve= 0 ,0
Exp/Cntr=0.3,0.1

Type RM Length L Ch R = 1 ,3989.4  ,336.4,344,351.6
XS GIS Cut Line= 2
      1793550.95      151245.108     1793671.917      151046.257
#Sta/Elev= 26
     9.7 1481.11    19.4 1481.37    29.1 1481.98    38.8 1480.45    48.5 1475.41
    58.2 1468.06    67.9  1460.6    77.6 1452.97    87.3 1444.55      97 1437.22
   106.7 1433.01   111.4 1432.71   116.4  1432.4   121.4 1432.74   126.1 1433.07
   135.8 1433.82   145.5  1434.8   155.2 1436.69   164.9 1439.36   174.6 1441.97
   184.3 1444.44     194 1445.85   203.7 1446.64   213.4 1446.57   223.1 1446.23
   232.8 1446.26
#Mann= 3 , 0 , 0
       0     .06       0   111.4    .045       0   121.4     .06       0
Bank Sta=111.4,121.4
XS Rating Curve= 0 ,0
Exp/Cntr=0.3,0.1

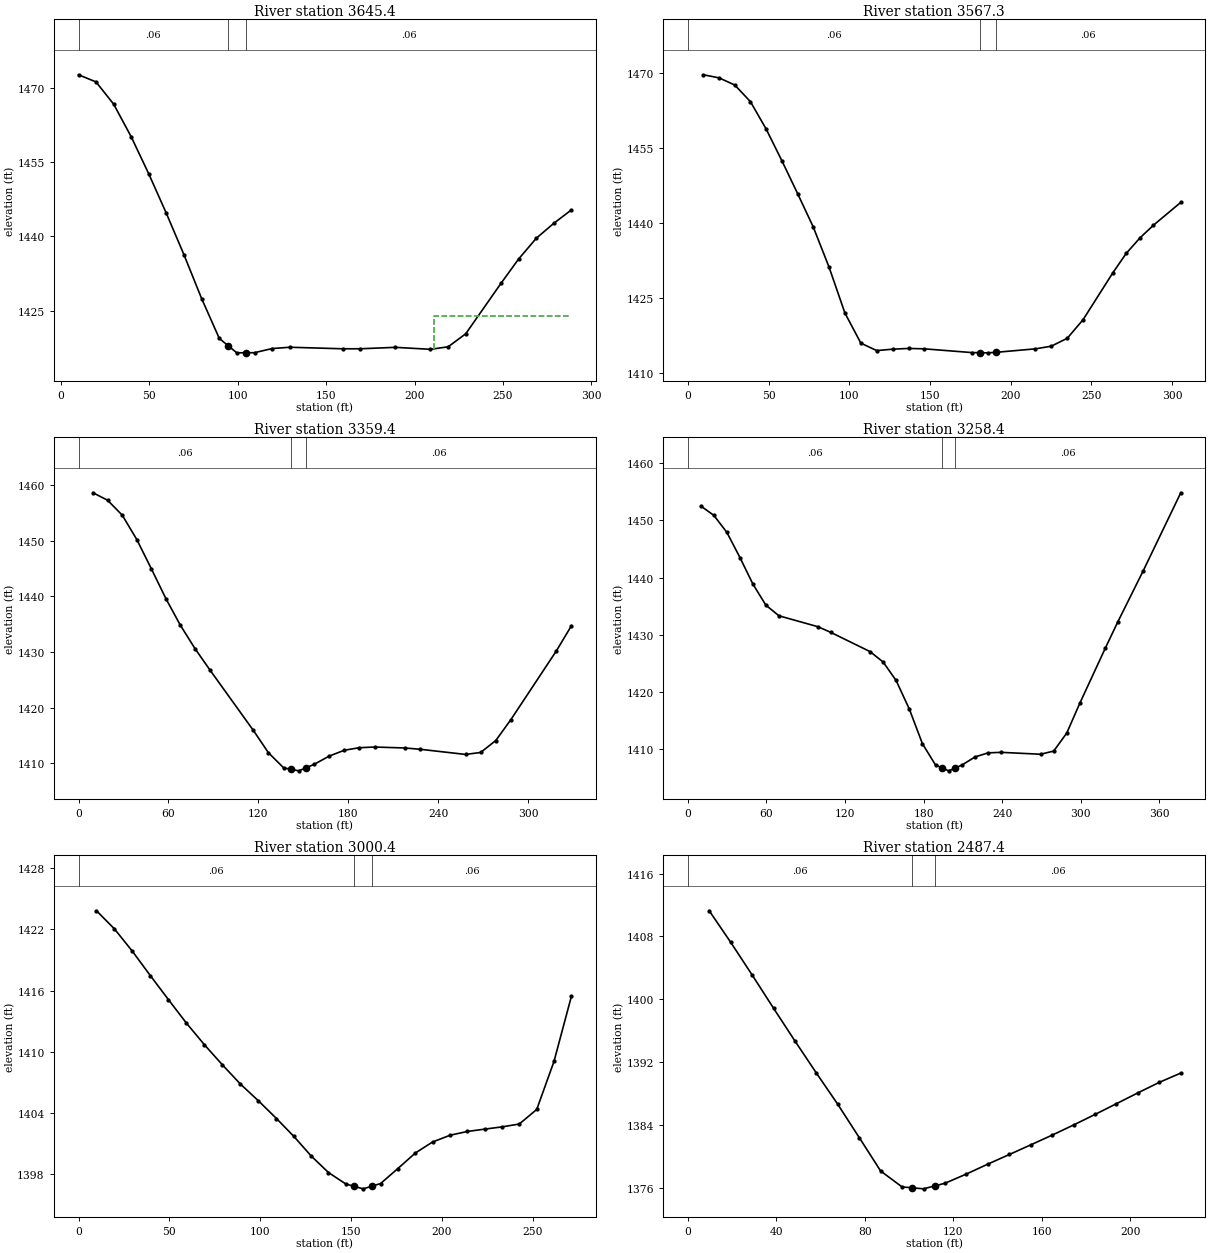
Type RM Length L Ch R = 1 ,3645.4  ,78.9,78.1,77.2
XS GIS Cut Line= 2
     1793787.914      151424.074     1794018.249      151250.079
#Sta/Elev= 26
      10 1472.63    19.9 1471.19    29.9 1466.69    39.8 1460.11    49.8 1452.57
    59.7 1444.64    69.7 1436.24    79.6 1427.47    89.6 1419.42    94.5 1417.98
    99.5 1416.51   104.5 1416.53   109.5 1416.54   119.4 1417.37   129.4 1417.64
   159.3 1417.33   169.2 1417.33   189.1 1417.62     209 1417.22     219 1417.73
   228.9 1420.35   248.9 1430.56   258.8 1435.44   268.8 1439.63   278.7 1442.65
   288.7 1445.37
#Mann= 3 , 0 , 0
      10     .06       0    94.5    .045       0   104.5     .06       0
#XS Ineff= 2 , 0
                          210.99         1423.93
Permanent Ineff=
       F       F
Bank Sta=94.5,104.5
XS Rating Curve= 0 ,0
Exp/Cntr=0.3,0.1

Type RM Length L Ch R = 1 ,3567.3  ,217.4,207.9,198.3
XS GIS Cut Line= 4
     1793810.225      151474.299     1793884.367      151451.161
     1794021.146      151338.859     1794060.445      151306.933
#Sta/Elev= 28
     9.7 1469.74    19.4 1469.12    29.1 1467.69    38.8 1464.36    48.5  1458.9
    58.3 1452.53      68 1445.98    77.7  1439.3    87.5 1431.25    97.3  1422.1
   107.2 1416.06     117 1414.58   126.8 1414.86   136.7 1415.01   146.5 1414.93
     176 1414.18   180.8 1414.16   185.8 1414.13   190.8 1414.23   215.3 1414.93
   225.1 1415.46     235 1417.04   244.8 1420.76   263.1 1430.07   271.5 1434.01
     280 1437.11   288.4 1439.66   305.3 1444.22
#Mann= 3 , 0 , 0
       0     .06       0   180.8    .045       0   190.8     .06       0
Bank Sta=180.8,190.8
XS Rating Curve= 0 ,0
Exp/Cntr=0.3,0.1

Type RM Length L Ch R = 1 ,3359.4  ,101.7,101,100.5
XS GIS Cut Line= 3
     1793984.101      151652.574     1794040.252       151550.35
     1794122.319      151354.541
#Sta/Elev= 28
     9.7 1458.61    19.4 1457.27    29.2 1454.58    38.9  1450.2    48.6 1444.95
    58.3 1439.59      68 1434.78    77.8 1430.57    87.5 1426.83   116.6 1415.92
   126.7 1411.89   136.9 1409.16     142 1408.89     147 1408.63     152  1409.2
   157.1 1409.78   167.2 1411.27   177.3 1412.33   187.4 1412.79   197.5 1412.91
   217.7 1412.74   227.8 1412.51   258.2 1411.58   268.3 1411.93   278.4 1414.08
   288.5 1417.85   318.8 1430.18   328.9 1434.72
#Mann= 3 , 0 , 0
       0     .06       0     142    .045       0     152     .06       0
Bank Sta=142,152
XS Rating Curve= 0 ,0
Exp/Cntr=0.3,0.1

Type RM Length L Ch R = 1 ,3258.4  ,250.3,258,265.7
XS GIS Cut Line= 4
     1794057.232      151697.892     1794140.739      151562.554
     1794191.685      151431.819     1794183.932      151355.226
#Sta/Elev= 30
     9.9 1452.52    19.9 1450.87    29.8 1447.91    39.8 1443.51    49.7 1438.87
    59.6 1435.19    69.6 1433.33    99.4 1431.42   109.3 1430.42   139.1 1427.08
   149.1 1425.26     159 1422.04   169.1 1417.04   179.1 1410.99   189.1 1407.27
   194.1 1406.76   199.1 1406.25   204.1 1406.75   209.1 1407.24   219.2 1408.67
   229.2 1409.39   239.2 1409.48   269.3 1409.15   279.3  1409.7   289.3 1412.86
   299.3 1418.09   318.6 1427.63   328.2 1432.25   347.5 1441.13   376.3 1454.82
#Mann= 3 , 0 , 0
       0     .06       0   194.1    .045       0   204.1     .06       0
Bank Sta=194.1,204.1
XS Rating Curve= 0 ,0
Exp/Cntr=0.3,0.1

Type RM Length L Ch R = 1 ,3000.4  ,527.1,513,498.8
XS GIS Cut Line= 4
      1794316.55      151679.478     1794357.884      151578.727
      1794416.01      151515.434      1794447.01      151445.684
#Sta/Elev= 30
     9.9 1423.81    19.8 1422.03    29.7 1419.83    39.6 1417.44    49.5  1415.1
    59.4  1412.8    69.3 1410.68    79.2 1408.71    89.1 1406.83      99 1405.19
   108.9 1403.46   118.4 1401.72     128 1399.79   137.5 1398.17   147.1 1397.04
   151.6 1396.82   156.6 1396.57   161.6 1396.84   166.2 1397.09   175.7 1398.56
   185.3 1400.08   194.8 1401.16   204.4 1401.82   213.9 1402.19   223.5 1402.42
     233 1402.64   242.5 1402.92   252.1 1404.35   261.6 1409.06   271.2 1415.46
#Mann= 3 , 0 , 0
       0     .06       0   151.6    .045       0   161.6     .06       0
Bank Sta=151.6,161.6
XS Rating Curve= 0 ,0
Exp/Cntr=0.3,0.1

Type RM Length L Ch R = 1 ,2487.4  ,447.1,448,448.9
XS GIS Cut Line= 2
     1794834.514      151780.229     1794852.597       151558.06
#Sta/Elev= 25
     9.7 1411.26    19.4 1407.25    29.1 1403.09    38.8 1398.85    48.5 1394.67
    58.1 1390.63    67.8 1386.64    77.5 1382.41    87.2 1378.15    96.9 1376.12
   101.6 1376.01   106.6 1375.88   111.6 1376.25   116.3 1376.59     126 1377.77
   135.7 1379.03   145.4 1380.25   155.1 1381.48   164.8 1382.72   174.4    1384
   184.1 1385.34   193.8 1386.71   203.5 1388.09   213.2 1389.43   222.9 1390.61
#Mann= 3 , 0 , 0
       0     .06       0   101.6    .045       0   111.6     .06       0
Bank Sta=101.6,111.6
XS Rating Curve= 0 ,0
Exp/Cntr=0.3,0.1

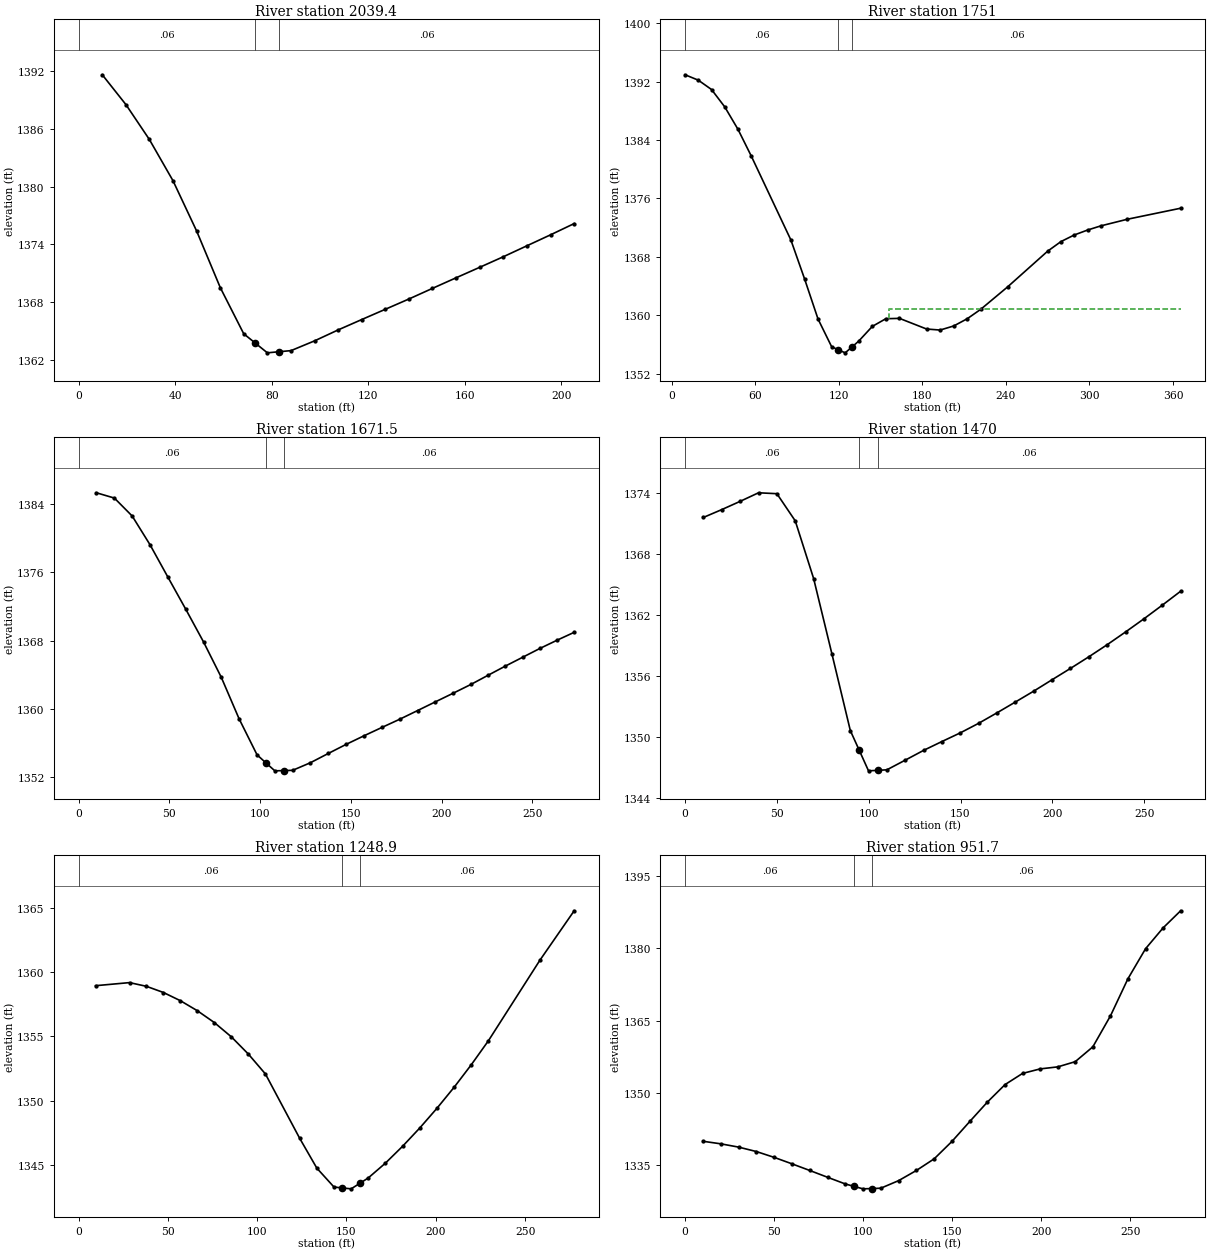
Type RM Length L Ch R = 1 ,2039.4  ,284.3,288.4,292.5
XS GIS Cut Line= 2
     1795276.899      151806.395      1795302.56      151602.708
#Sta/Elev= 23
     9.8 1391.63    19.6 1388.53    29.3 1384.91    39.1 1380.62    48.9 1375.39
    58.7 1369.51    68.4 1364.72    73.2 1363.75    78.2 1362.74    83.2 1362.86
      88 1362.97    97.8 1363.99   107.5 1365.12   117.3  1366.2   127.1 1367.27
   136.9 1368.34   146.6 1369.44   156.4 1370.54   166.2 1371.63     176 1372.73
   185.7 1373.86   195.5    1375   205.3 1376.17
#Mann= 3 , 0 , 0
       0     .06       0    73.2    .045       0    83.2     .06       0
Bank Sta=73.2,83.2
XS Rating Curve= 0 ,0
Exp/Cntr=0.3,0.1

Type RM Length L Ch R = 1 ,1751    ,81.6,79.5,77.4
XS GIS Cut Line= 4
     1795483.837      151881.575     1795552.946      151831.183
     1795600.459      151692.965     1795619.176      151560.506
#Sta/Elev= 30
     9.5 1392.93      19 1392.19    28.5 1390.91      38 1388.53    47.5 1385.46
      57 1381.82    85.5 1370.31    95.3    1365     105 1359.49   114.8 1355.69
   119.5 1355.28   124.5 1354.86   129.5 1355.68   134.2 1356.46     144 1358.48
   153.7 1359.53   163.5 1359.58     183 1358.12   192.7 1357.98   202.5 1358.54
   212.2 1359.53   221.9 1360.82   241.2 1363.89   269.9 1368.77   279.5 1370.09
     289 1370.99   298.6 1371.67   308.1 1372.24   327.2 1373.15   365.5 1374.66
#Mann= 3 , 0 , 0
     9.5     .06       0   119.5    .045       0   129.5     .06       0
#XS Ineff= 2 , 0
                          155.84         1360.91
Permanent Ineff=
       F       F
Bank Sta=119.5,129.5
XS Rating Curve= 0 ,0
Exp/Cntr=0.3,0.1

Type RM Length L Ch R = 1 ,1671.5  ,207.1,201.5,195.8
XS GIS Cut Line= 3
     1795618.563      151917.147     1795667.647      151706.603
     1795666.355      151649.769
#Sta/Elev= 30
     9.8 1385.31    19.7 1384.69    29.5 1382.59    39.3 1379.24    49.1 1375.47
      59 1371.69    68.8 1367.86    78.6 1363.71    88.4 1358.86    98.3 1354.64
   103.1 1353.72   108.1 1352.77   113.1  1352.8   117.9 1352.83   127.7 1353.72
   137.6 1354.81   147.4 1355.87   157.2 1356.87   167.1 1357.85   176.9 1358.81
   186.7 1359.82   196.5 1360.84   206.4 1361.86   216.2 1362.89   225.7 1363.97
   235.1 1365.03   244.6 1366.06   254.1 1367.09   263.6 1368.06     273 1368.98
#Mann= 3 , 0 , 0
       0     .06       0   103.1    .045       0   113.1     .06       0
Bank Sta=103.1,113.1
XS Rating Curve= 0 ,0
Exp/Cntr=0.3,0.1

Type RM Length L Ch R = 1 ,1470    ,206.3,221.1,236
XS GIS Cut Line= 2
     1795842.874      151957.189     1795828.618      151687.711
#Sta/Elev= 29
      10 1371.59      20 1372.36      30 1373.17      40 1374.01      50 1373.92
      60 1371.25      70 1365.59      80 1358.16      90 1350.65    94.9  1348.7
    99.9  1346.7   104.9 1346.75   109.9  1346.8   119.9 1347.75   129.9 1348.71
   139.9 1349.58   149.9 1350.43   159.9 1351.37   169.9  1352.4   179.9 1353.46
   189.9 1354.53   199.9 1355.65   209.9 1356.76   219.9  1357.9   229.9 1359.09
   239.9 1360.34   249.9 1361.63   259.9 1362.97   269.9 1364.34
#Mann= 3 , 0 , 0
       0     .06       0    94.9    .045       0   104.9     .06       0
Bank Sta=94.9,104.9
XS Rating Curve= 0 ,0
Exp/Cntr=0.3,0.1

Type RM Length L Ch R = 1 ,1248.9  ,294,297.2,300.4
XS GIS Cut Line= 3
     1796020.232      151986.234     1796020.497      151881.667
     1796129.444      151747.349
#Sta/Elev= 26
     9.5 1358.94    28.5 1359.18      38 1358.89    47.5 1358.41      57 1357.77
    66.5 1356.99      76 1356.07    85.6 1354.95    95.1 1353.61   104.6 1352.07
   123.8 1347.06   133.4 1344.74     143 1343.27   147.6  1343.2   152.6 1343.13
   157.6 1343.57   162.2 1343.98   171.8 1345.13   181.4 1346.44     191 1347.86
   200.6 1349.39   210.3 1351.04   219.9 1352.79   229.5 1354.66   258.3 1360.92
   277.5 1364.77
#Mann= 3 , 0 , 0
       0     .06       0   147.6    .045       0   157.6     .06       0
Bank Sta=147.6,157.6
XS Rating Curve= 0 ,0
Exp/Cntr=0.3,0.1

Type RM Length L Ch R = 1 ,951.7   ,553.3,544.8,536.3
XS GIS Cut Line= 3
     1796222.441      152073.065     1796339.062      151963.642
     1796441.452      151904.138
#Sta/Elev= 30
      10 1339.96      20 1339.43      30 1338.75      40 1337.83      50 1336.62
      60 1335.28      70  1333.9      80 1332.49      90  1331.1    94.9  1330.6
    99.9 1330.09   104.9 1330.15   109.9 1330.22   119.9 1331.79   129.9  1333.9
   139.9 1336.32   149.9 1339.94   159.9 1344.07   169.8  1348.1   179.7 1351.72
   189.5 1354.03   199.4 1354.97   209.3 1355.39   219.1 1356.47     229 1359.55
   238.9 1365.98   248.7 1373.67   258.6  1379.9   268.5 1384.24   278.3 1387.77
#Mann= 3 , 0 , 0
       0     .06       0    94.9    .045       0   104.9     .06       0
Bank Sta=94.9,104.9
XS Rating Curve= 0 ,0
Exp/Cntr=0.3,0.1

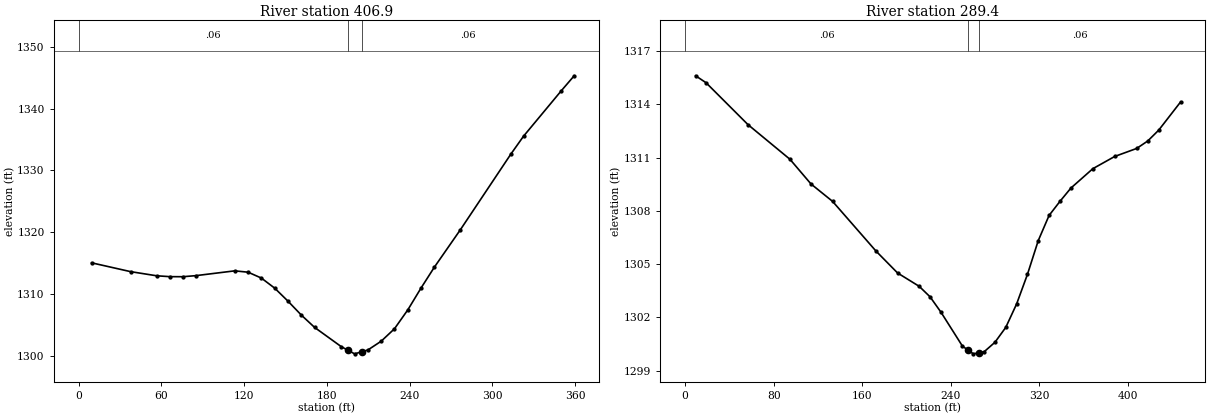
Type RM Length L Ch R = 1 ,406.9   ,117.3,117.5,117.8
XS GIS Cut Line= 4
     1796689.794      152402.791     1796750.503      152307.206
     1796813.795      152166.413     1796815.087      152074.704
#Sta/Elev= 28
     9.4 1315.02    37.7 1313.59    56.6 1312.92    66.1 1312.78    75.5 1312.77
    84.9 1312.94   113.2 1313.72   122.9  1313.5   132.5 1312.55   142.2 1310.91
   151.8 1308.81   161.5 1306.55   171.1 1304.56   190.4 1301.45   195.1 1300.88
   200.1 1300.28   205.1  1300.6   209.7  1300.9   219.4 1302.33     229 1304.34
   238.7 1307.41   248.3 1310.95     258 1314.34   276.8 1320.38   313.5 1332.66
   322.6 1335.53   350.1 1342.92   359.3 1345.31
#Mann= 3 , 0 , 0
       0     .06       0   195.1    .045       0   205.1     .06       0
Bank Sta=195.1,205.1
XS Rating Curve= 0 ,0
Exp/Cntr=0.3,0.1

Type RM Length L Ch R = 1 ,289.4   ,287.8,289.4,290.9
XS GIS Cut Line= 4
     1796738.316      152477.386     1796830.025      152410.219
     1796924.318      152206.133     1796934.651      152097.632
#Sta/Elev= 30
     9.5  1315.6    18.9 1315.21    56.8 1312.85    94.7  1310.9   113.7 1309.51
   133.2 1308.53   172.3 1305.74   191.9  1304.5   211.4 1303.75   221.2 1303.16
     231  1302.3   250.5 1300.38   255.3 1300.17   260.3 1299.95   265.3 1300.01
   270.1 1300.07   279.8  1300.6   289.6 1301.44   299.4 1302.76   309.2 1304.43
   318.9 1306.32   328.7 1307.74   338.5 1308.53   348.4 1309.28   368.2 1310.37
     388 1311.06   407.8 1311.51   417.8 1311.93   427.7 1312.54   447.5 1314.13
#Mann= 3 , 0 , 0
       0     .06       0   255.3    .045       0   265.3     .06       0
Bank Sta=255.3,265.3
XS Rating Curve= 0 ,0
Exp/Cntr=0.3,0.1

Chan Stop Cuts=-1
Use User Specified Reach Order=0